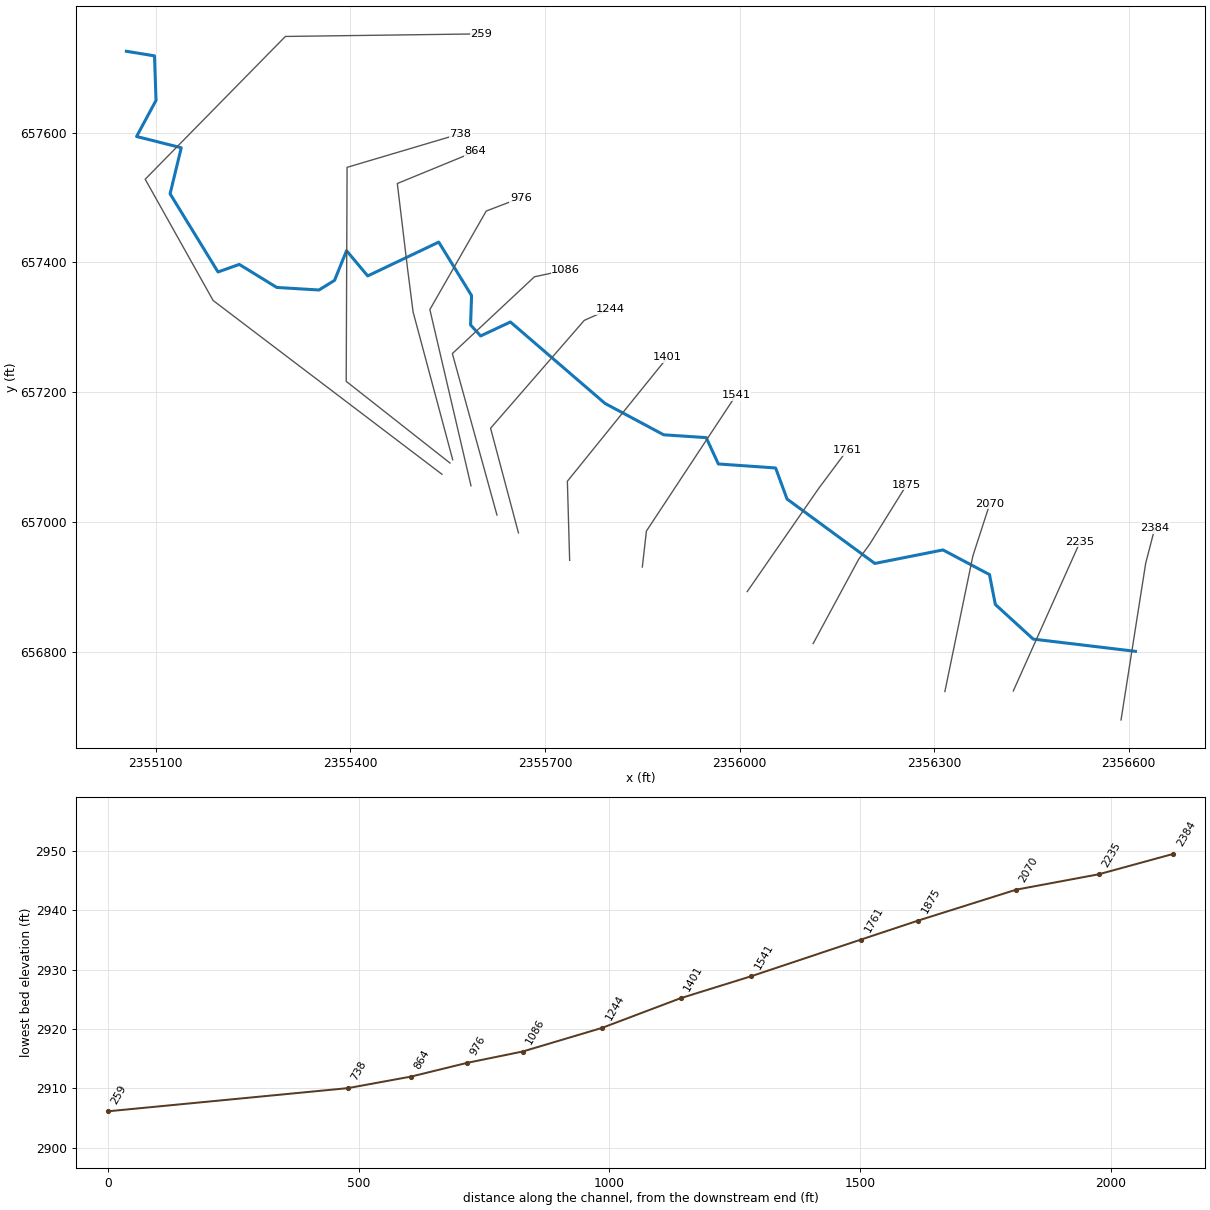
--- LAURELFKT2.prj (project) ---

Proj Title=LAURELFKT2
Current Plan=p01
Default Exp/Contr=0,0
English Units
Geom File=g01
Flow File=f01
Plan File=p01
Background Map Layer=Inundation Boundary (P100yr Value_0)
BEGIN DESCRIPTION:
----------MODEL BY WOOD PLC 2022----------
AFH study
Randolph County, WV
HEC-RAS Version: RAS 6.2
Vertical Datum: NAVD88
Projection: NAD 1983 StatePlane West Virginia S FIPS 4702 (US Feet)
Terrain: 1-meter LIDAR (FEMA Region III 3DEP collected 2016-2018)
Land Use: 2019 NLCD
Hydrologic Method:
WV SIR2010-5033 regression equations
Additional Model Notes:
Split flows from RS 1244 to 1875
END DESCRIPTION:
DSS Export Rating Curves= 0
DSS Export Rating Curve Sorted= 0
DSS Export Volume Flow Curves= 0
DXF OffsetX= 0
DXF OffsetY= 0
DXF ScaleX= 0
DXF ScaleY= 0

--- LAURELFKT2.p01 (plan) ---

Plan Title=Floodplain
Program Version=6.20
Short Identifier=Floodplain
Geom File=g01
Flow File=f01
Subcritical Flow
K Sum by GR= 0
Std Step Tol= 0.01
Critical Tol= 0.01
Num of Std Step Trials= 20
Max Error Tol= 0.3
Flow Tol Ratio= 0.001
Split Flow NTrial= 30
Split Flow Tol= 0.02
Split Flow Ratio= 0.02
Log Output Level= 0
Friction Slope Method= 1
Unsteady Friction Slope Method= 2
Unsteady Bridges Friction Slope Method= 1
Parabolic Critical Depth
Global Vel Dist= 0 , 0 , 0
Global Log Level= 0
CheckData=False
Encroach Param=-1 ,0,0, 0
Mapping Interval=1HOUR
Computation Time Step Use Courant=        0
Computation Time Step Use Time Series=    0
Computation Time Step Count To Double=0
Computation Time Step Max Doubling=0
Computation Time Step Max Halving=0
Computation Time Step Residence Courant=0
Run HTab= 0
Run UNet= 0
Run Sediment= 0
Run PostProcess= 0
Run WQNet= 0
Run RASMapper=-1
UNET Theta= 0
UNET Theta Warmup= 0
UNET ZTol= 0
UNET ZSATol= 0
UNET MxIter= 0
UNET Max Iter WO Improvement= 0
UNET MaxInSteps= 0
UNET DtIC= 0
UNET DtMin= 0
UNET MaxCRTS= 0
UNET WFStab= 0
UNET SFStab= 0
UNET WFX= 1
UNET SFX= 1
UNET Gravity=32.174
UNET 1D Methodology=Finite Difference
UNET DSS MLevel= 1
UNET Pardiso=0
UNET DZMax Abort= 0
UNET Use Existing IB Tables= 0
UNET Froude Reduction=False
UNET Froude Limit= 0
UNET Froude Power= 0
UNET D1 Cores= 0
UNET WindReference=Eulerian
UNET WindDragFormulation=Hsu (1988)
UNET D2 Coriolis=0
UNET D2 Cores= 0
UNET D2 Theta= 1
UNET D2 Theta Warmup= 1
UNET D2 Z Tol= 0.01
UNET D2 Volume Tol= 0.01
UNET D2 Max Iterations= 20
UNET D2 Equation= 0
UNET D2 RampUpFraction=0.1
UNET D2 TimeSlices= 1
UNET D2 Turbulence Formulation=Non-Conservative (original)
UNET D2 Eddy Viscosity=0.3
UNET D2 Transverse Eddy Viscosity=0.1
UNET D2 Smagorinsky Mixing=0
UNET D2 BCVolumeCheck=0
UNET D2 Cores=0
UNET D2 SolverType=PARDISO (Direct)
UNET D2 Minimum Iterations= 2147483647
UNET D2 Maximum Iterations= 2147483647
UNET D2 Restart Number= 10
UNET D2 Relaxation Coeff=1.3
UNET D2 SOR Precondition Iterations= 10
UNET D2 ILUT Maximum Fill= 8
UNET D2 ILUT Tolerance=1E-08
UNET D1D2 MaxIter= 0
UNET D1D2 ZTol=0.01
UNET D1D2 QTol=0.1
UNET D1D2 MinQTol=1
Write IC File= 0
Write IC File at Fixed DateTime=0
Write IC File at Sim End=0
Echo Input=False
Echo Parameters=False
Echo Output=False
Write Detailed= 0
HDF Write Warmup=0
HDF Write Time Slices=0
HDF Flush=0
HDF Compression= 1
HDF Chunk Size= 1
HDF Spatial Parts= 1
HDF Use Max Rows=0
HDF Fixed Rows= 1
Calibration Method= 0
Calibration Iterations= 20
Calibration Max Change=0.05
Calibration Tolerance=0.2
Calibration Maximum=1.5
Calibration Minimum=0.5
Calibration Optimization Method= 1
WQ AD Non Conservative
WQ ULTIMATE=-1
WQ Max Comp Step=1HOUR
WQ Output Interval=15MIN
WQ Output Selected Increments= 0
WQ Output face flow=0
WQ Output face velocity=0
WQ Output face area=0
WQ Output face dispersion=0
WQ Output cell volume=0
WQ Output cell surface area=0
WQ Output cell continuity=0
WQ Output cumulative cell continuity=0
WQ Output face conc=0
WQ Output face dconc_dx=0
WQ Output face courant=0
WQ Output face peclet=0
WQ Output face adv mass=0
WQ Output face disp mass=0
WQ Output cell mass=0
WQ Output cell source sink temp=0
WQ Output nsm pathways=0
WQ Output nsm derived pathways=0
WQ Create Restart=0
WQ Fixed Restart=0
WQ System Summary=0
WQ Write To DSS=0
Sorting and Armoring Iterations= 10
XS Update Threshold= 0.02
Bed Roughness Predictor= 0
Hydraulics Update Threshold= 0.02
Energy Slope Method= 1
Volume Change Method= 1
Sediment Retention Method= 0
Sediment TS Multiplier= 1
Warm Up Method= 0
XS Weighting Method= 0
Number of US Weighted Cross Sections= 1
Number of DS Weighted Cross Sections= 1
Upstream XS Weight=0
Main XS Weight=1
Downstream XS Weight=0
Number of DS XS's Weighted with US Boundary= 1
Upstream Boundary Weight= 1
Weight of XSs Associated with US Boundary= 0
Number of US XS's Weighted with DS Boundary= 1
Downstream Boundary Weight= 0.5
Weight of XSs Associated with DS Boundary= 0.5
Percentile Method= 0
Sediment Output Level= 3
Mass or Volume Output= 0
Output Increment Type= 1
Profile and TS Output Increment= 1
Transport Output Increment 1
XS Output Flag= 0
XS Output Increment= 10
Read HDF5 Sediment Hotstart= 0
Sediment Hotstart Type= 0
Write Gradation File= 0
Read Gradation Hotstart= 0
Write HDF5 File= 1
Write Binary Output= 1
Write DSS Sediment File= 0
DSS Sediment Output Type= 1
SV Curve= 0
Specific Gage Flag= 0
Subcell Erosion Methods= 0
Subcell Deposition Methods= 0
Advection Scheme= 1
Matrix Solver= 0
Implicit Weighting Factor= 1
Maximum Outer Loop Convergence Iterations= 5
Convergence Maximum Absolute= 0.001
Convergence RMSE= 0.0001
Grain Fractions Max Abs Error= 0.001
Max Subgrid Regions= 1
Max Subgrid Length Scale= 3.402823E+38
Initial Layer Thickness= 3.402823E+38
Min Layer Thickness= 3.402823E+38
Max Layer Thickness= 3.402823E+38
Number of Layers= 5

--- LAURELFKT2.f01 (steady flow) ---

Flow Title=Flow
Program Version=6.20
Number of Profiles= 1
Profile Names=P100yr
River Rch & RM=LAURELFKT2,Main,2384
     274
Boundary for River Rch & Prof#=LAURELFKT2,Main            , 1
Up Type= 0
Dn Type= 3
Dn Slope=0.026633
DSS Import GetInterval= 0
DSS Import GetPeak= 0
DSS Import FillOption= 0

--- LAURELFKT2.g01 (geometry) ---

Geom Title=Geometry
Program Version=6.20

River Reach=LAURELFKT2      ,Main
Reach XY= 30
2356610.37800002656800.3860000222356452.71926441656819.269127032
2356394.33200003656872.6810000092356385.32373676656918.750085306
2356313.63000001656956.7460000222356208.54038625656935.928917399
     2356073.206657035.2060000152356055.55200002657083.122999996
2355967.28500001657089.2870000152355948.51000002657129.918000013
      2355883.03657134.2559999972355792.46400002657182.677000016
2355646.66300002657308.214000002     2355600.752657286.693000004
2355585.21877789657303.6612221342355586.76400003657348.923000008
2355536.15866665 657431.36686539     2355426.616657379.231000006
2355393.97599998      657418.1472355375.50400002657372.417000011
2355351.47300002657357.531000018     2355286.374657361.476999998
     2355228.627657396.986000001     2355195.808657385.329000011
2355121.92100003657505.8439999972355139.13800001657576.861000001
2355070.27200001657594.2570000142355100.22100003657649.852000013
2355097.89000003657718.5380000172355054.49542118657725.604079096

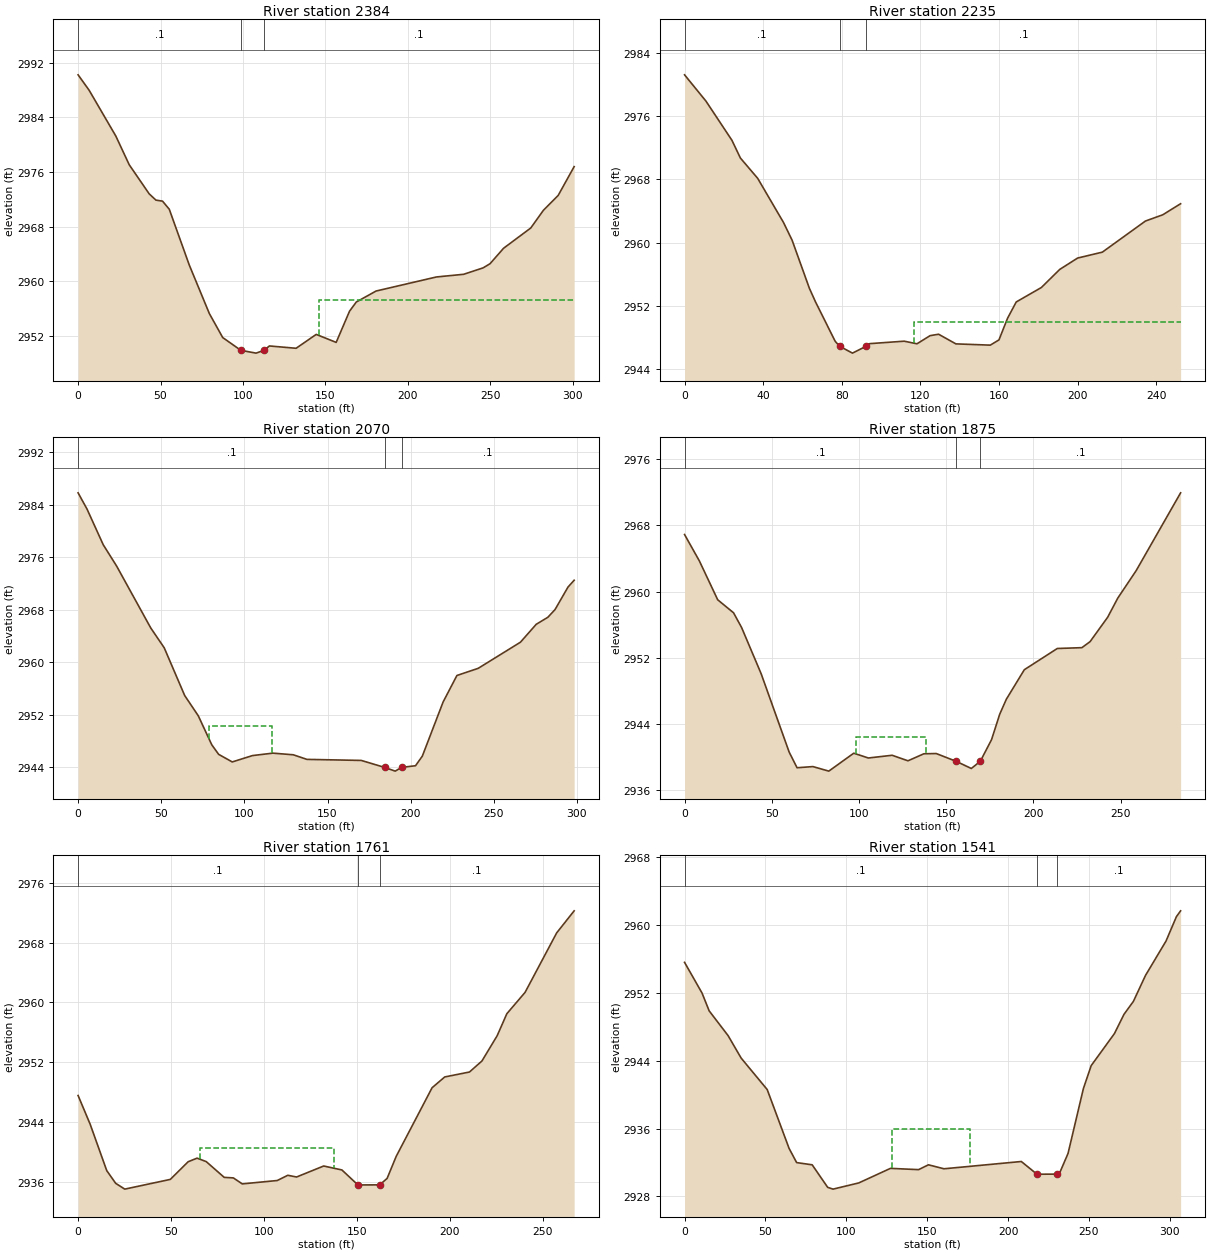
Type RM Length L Ch R = 1 ,2384    ,150.7,149.2,147.2
XS GIS Cut Line= 3
 2356588.1313696656694.5655012062356626.19002351656936.308432498
2356640.28582125656990.577253809
#Sta/Elev= 30
       0 2990.21     6.7 2987.95    22.9 2981.24      31 2977.05    43.1 2972.79
    47.2 2971.87    51.2 2971.72    55.3 2970.53    67.4 2962.38    79.6 2955.26
    87.7 2951.75   98.712949.877   107.9 2949.47  112.742949.876     116 2950.52
   132.2 2950.18   144.4 2952.21   156.5 2951.04   164.6 2955.61   168.7 2956.95
   180.7 2958.56   217.3 2960.62   233.8 2961.01   245.6 2961.95   249.8 2962.56
     258 2964.82   274.5 2967.79   282.2 2970.39   291.1 2972.55   300.8 2976.77
#Mann= 3 ,-1,0
       0      .1       0   98.71    .045       0  112.74      .1       0
#XS Ineff= 1 ,-1
  145.82  300.79 2957.26
Permanent Ineff=
       F
Bank Sta=98.71,112.74
XS Rating Curve= 0 ,0
Exp/Cntr(USF)=0,0
Exp/Cntr=0.3,0.1

Type RM Length L Ch R = 1 ,2235    ,163.7,164.5,163.8
XS GIS Cut Line= 2
2356421.99444225 656739.227021442356525.11246207656969.508518634
#Sta/Elev= 30
       0 2981.22    10.9 2977.89    24.1 2972.94    28.4  2970.7    37.2 2968.13
    50.3 2962.56    54.7 2960.31    63.5 2954.22    66.7 2952.46    76.6 2947.53
   78.812946.908    85.4 2946.03    92.42946.906    94.2 2947.23   111.7 2947.54
   118.2 2947.21   124.9 2948.24   129.2 2948.42     138  2947.2   155.5 2947.04
   159.9  2947.7   164.3 2950.45   168.7  2952.5   181.5 2954.33   190.8 2956.61
   199.9 2958.05   212.5  2958.8   234.4 2962.73   243.2 2963.52   252.3 2964.92
#Mann= 3 ,-1,0
       0      .1       0   78.81    .045       0    92.4      .1       0
#XS Ineff= 2 , 0
                          116.68         2949.97
Permanent Ineff=
       F       F
Bank Sta=78.81,92.4
XS Rating Curve= 0 ,0
Exp/Cntr(USF)=0,0
Exp/Cntr=0.3,0.1

Type RM Length L Ch R = 1 ,2070    ,195.7,195.1,189
XS GIS Cut Line= 3
2356316.55193128656738.4180984852356359.71044481656947.531372372
2356385.91382803657028.196689326
#Sta/Elev= 30
       0 2985.84     5.4 2983.35    15.1 2977.94    23.2 2974.67    43.7 2965.25
    51.8 2962.23    64.1 2954.96    72.3 2951.86    80.4 2947.45    84.5    2946
    92.7 2944.84   104.9 2945.81   117.1 2946.18   129.4 2945.93   137.6 2945.23
   170.3 2945.07  184.372944.002   190.7 2943.44   194.5 2944.01   202.9 2944.26
     207 2945.72   219.5 2953.97   227.8 2958.01   240.6  2959.1     266 2963.08
   275.5 2965.81   282.5 2966.88   286.8 2968.05   294.6 2971.48   298.3 2972.52
#Mann= 3 ,0,0
       0      .1       0  184.37    .045       0   194.5      .1       0
#XS Ineff= 1 ,-1
   78.86  116.85 2950.24
Permanent Ineff=
       F
Bank Sta=184.37,194.5
XS Rating Curve= 0 ,0
Exp/Cntr(USF)=0,0
Exp/Cntr=0.3,0.1

Type RM Length L Ch R = 1 ,1875    ,113.7,114.1,114
XS GIS Cut Line= 4
2356113.46696692656812.4159034582356183.45964762656942.099575315
2356200.77730048656965.7869395722356257.66202682657057.235191797
#Sta/Elev= 30
       0  2966.9     8.5  2963.7      19    2959    28.1 2957.42    32.7 2955.64
    43.9 2950.05      60 2940.54    64.5 2938.66    73.6  2938.8    82.7 2938.25
      97 2940.42   105.4 2939.84     119 2940.17   128.1  2939.5   137.2 2940.35
   144.3 2940.38   155.8 2939.43   164.4 2938.57  169.572939.443     176 2942.06
   180.7 2945.15   184.5 2946.96   194.8 2950.53   213.7  2953.1   227.8  2953.2
   232.5 2953.93   242.6 2956.89   248.4 2959.21   258.9 2962.52   284.4 2971.95
#Mann= 3 ,-1,0
       0      .1       0   155.8    .045       0  169.57      .1       0
#XS Ineff= 1 ,-1
   98.36  138.55 2942.34
Permanent Ineff=
       F
Bank Sta=155.8,169.57
XS Rating Curve= 0 ,0
Exp/Cntr(USF)=0,0
Exp/Cntr=0.3,0.1

Type RM Length L Ch R = 1 ,1761    ,215.3,219.7,217
XS GIS Cut Line= 3
2356011.80442759656892.5548010912356122.32104974657052.087163602
2356165.78783836657110.351156866
#Sta/Elev= 30
       0 2947.56     6.5 2943.72    15.4 2937.53    20.2 2935.83    25.1 2935.05
    49.6 2936.35    59.2 2938.71      64 2939.19    68.9 2938.73    78.6 2936.62
    83.5 2936.55    88.3 2935.75   107.1  2936.2   112.8  2936.9   117.5 2936.67
   132.1 2938.14   141.9 2937.61  150.522935.608   162.2 2935.62   166.2 2936.48
   171.1 2939.43   190.4  2948.6   197.2 2950.04   210.5  2950.7   217.2 2952.17
   225.4 2955.55   230.6 2958.49   240.4 2961.34   257.4 2969.29   266.8 2972.24
#Mann= 3 ,-1,0
       0      .1       0  150.52    .045       0   162.2      .1       0
#XS Ineff= 1 ,-1
   65.46  137.37 2940.58
Permanent Ineff=
       F
Bank Sta=150.52,162.2
XS Rating Curve= 0 ,0
Exp/Cntr(USF)=0,0
Exp/Cntr=0.3,0.1

Type RM Length L Ch R = 1 ,1541    ,138.8,140.2,138.8
XS GIS Cut Line= 3
2355850.05267425656930.4378729492355856.33235214656985.813214383
2355994.48526582657195.326104136
#Sta/Elev= 30
       0 2955.62    10.8    2952    15.2  2949.9    26.9 2946.98      35 2944.32
    51.1 2940.61    64.6 2933.68    69.3 2931.99    78.9 2931.73    88.5 2929.07
    91.8 2928.86   107.7 2929.59   127.3 2931.31   144.7 2931.16   150.8 2931.73
   160.4 2931.26   208.2 2932.12   217.9 2930.62  230.13 2930.63   232.3 2930.94
   237.1 2933.07   246.6 2940.73   251.4 2943.43   265.8 2947.22   271.7 2949.49
   277.5 2951.01     285 2954.08   297.7 2958.14   304.1 2961.01   306.7  2961.7
#Mann= 3 ,-1,0
       0      .1       0   217.9    .045       0  230.13      .1       0
#XS Ineff= 1 ,-1
  128.01  176.29 2935.95
Permanent Ineff=
       F
Bank Sta=217.9,230.13
XS Rating Curve= 0 ,0
Exp/Cntr(USF)=0,0
Exp/Cntr=0.3,0.1

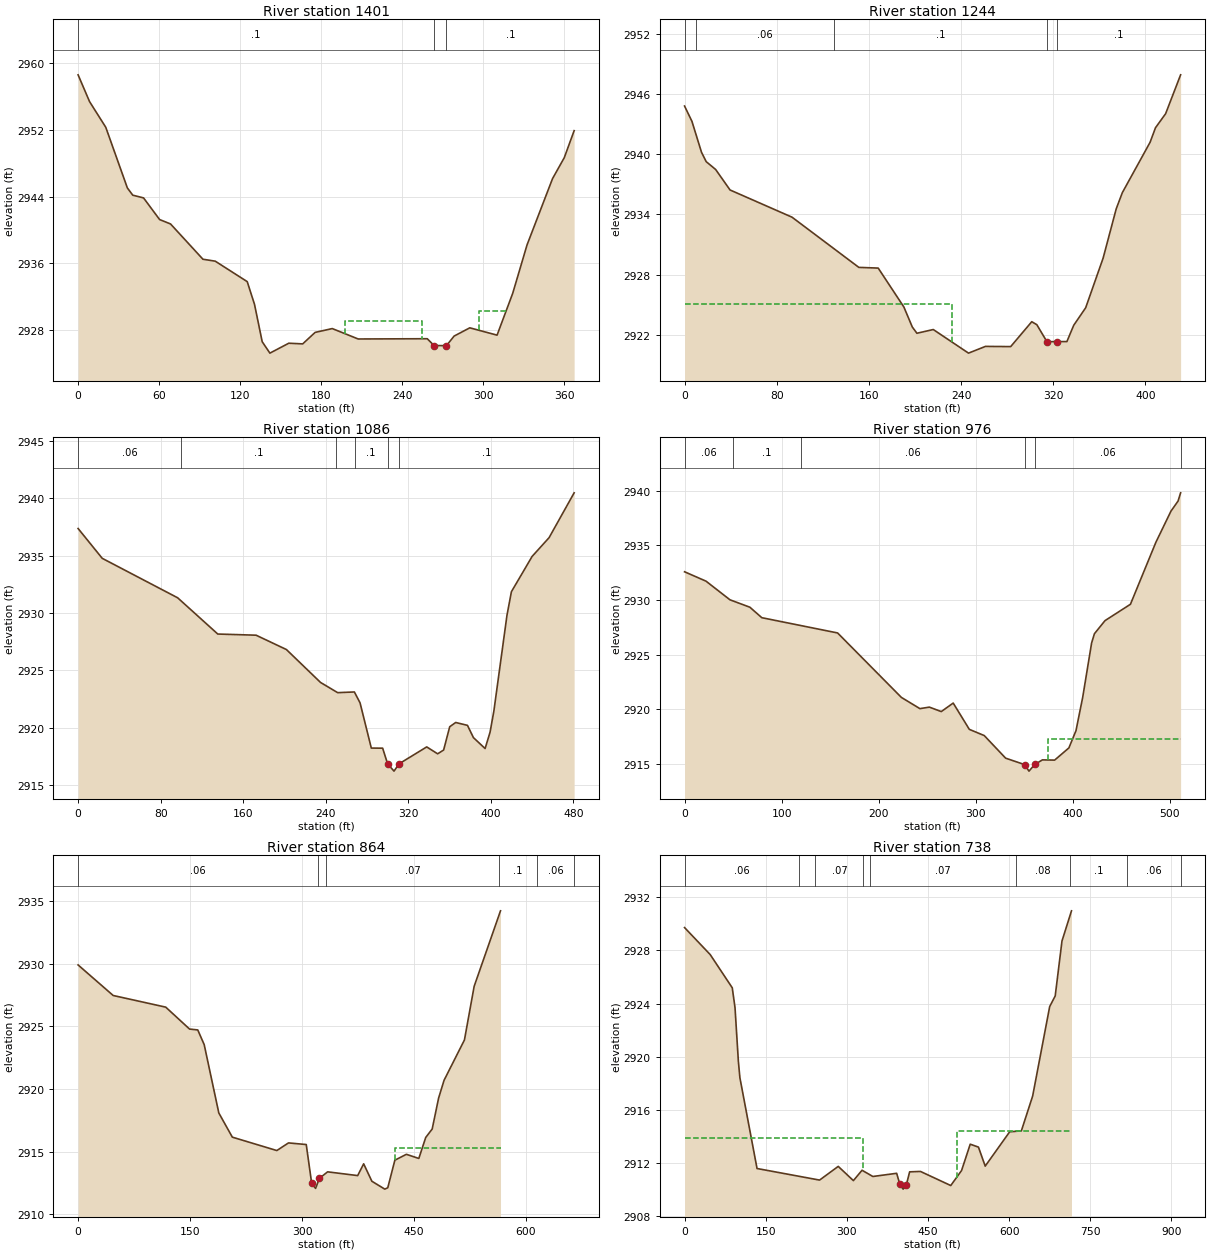
Type RM Length L Ch R = 1 ,1401    ,154.9,156.8,155.1
XS GIS Cut Line= 3
2355737.99108219656940.6996137062355734.46713276657062.628264183
2355888.81611804657253.626323601
#Sta/Elev= 30
       0 2958.62     8.5  2955.4    20.5 2952.32    36.5 2945.03    40.5 2944.16
    48.5 2943.83    60.4 2941.23    68.5  2940.7    92.5 2936.46   101.6 2936.23
   125.3 2933.77   130.7 2931.04   136.4 2926.55   142.1 2925.18   156.1 2926.37
   166.4 2926.29   175.6 2927.67   188.3 2928.13   207.5 2926.88   258.7 2926.91
  263.772926.087   272.9 2926.08   278.6 2927.23   290.2 2928.22   310.4 2927.34
     322 2932.37   332.6 2938.18   351.5 2946.15   360.2 2948.67   367.5 2951.91
#Mann= 3 ,-1,0
       0      .1       0  263.77    .045       0   272.9      .1       0
#XS Ineff= 2 ,-1
   197.4  254.61 2929.09  297.34  317.47 2930.28
Permanent Ineff=
       F       F
Bank Sta=263.77,272.9
XS Rating Curve= 0 ,0
Exp/Cntr(USF)=0,0
Exp/Cntr=0.3,0.1

Type RM Length L Ch R = 1 ,1244    ,155.4,158.1,154.9
XS GIS Cut Line= 4
2355659.05461483656982.9870069352355616.06243171657144.383891093
2355760.54435858 657310.714304462355800.01259226657328.334051639
#Sta/Elev= 30
       0 2944.79     6.4 2943.27    14.7 2940.19    18.8 2939.25      27 2938.47
    39.5 2936.43    93.3 2933.72   151.3 2928.72   168.1 2928.65   190.4 2924.77
   197.7 2922.78   201.7 2922.16   215.9 2922.53   246.5 2920.18   261.2 2920.85
   283.1 2920.83   301.4 2923.31   305.8 2923.01  314.572921.316   323.6 2921.33
   331.9 2921.33   337.8 2922.95   348.2  2924.7   363.3 2929.63   374.7 2934.55
     380 2936.16   404.1 2941.18   408.8 2942.63   417.6 2944.03   430.6  2947.9
#Mann= 5 ,-1,0
       0      .1       0      10     .06       0     130      .1       0
  314.57    .045       0   323.6      .1       0
#XS Ineff= 2 , 0
          232.24 2925.12
Permanent Ineff=
       F       F
Bank Sta=314.57,323.6
XS Rating Curve= 0 ,0
Exp/Cntr(USF)=0,0
Exp/Cntr=0.3,0.1

Type RM Length L Ch R = 1 ,1086    ,110.4,110.3,112.9
XS GIS Cut Line= 4
2355625.87747548657010.6435684022355557.13870871657259.495306334
2355683.65120306657377.873214136 2355731.9270832657388.277498647
#Sta/Elev= 30
       0 2937.36    23.4 2934.76    96.5 2931.32   135.4 2928.16   172.5 2928.06
   201.9 2926.81     235 2923.94   251.6 2923.05   267.8 2923.11   273.3 2922.16
   284.2 2918.22   295.2 2918.21  299.972916.853   306.2 2916.21  311.242916.854
   337.9 2918.32   348.5 2917.72   354.3 2918.05   360.2 2920.08     366 2920.45
   377.4  2920.2   383.2 2919.13   394.5 2918.18   399.3  2919.6     403 2921.45
   415.7  2929.8     420 2931.85   440.1 2934.93   456.5 2936.56   480.8 2940.47
#Mann= 6 ,-1,0
       0     .06       0     100      .1       0     250     .06       0
  268.17      .1       0  299.97    .045       0  311.24      .1       0
Bank Sta=299.97,311.24
XS Rating Curve= 0 ,0
Exp/Cntr(USF)=0,0
Exp/Cntr=0.3,0.1

Type RM Length L Ch R = 1 ,976     ,108.1,111.8,113.2
XS GIS Cut Line= 4
2355585.88534431657055.6284676012355522.45425446657327.364124092
2355609.37834055657479.2854997672355662.62913202657499.646096507
#Sta/Elev= 30
       0 2932.59    22.1 2931.73    46.8 2930.02    67.3 2929.34    79.6 2928.38
   157.7 2926.98   223.4 2921.07   242.5 2920.04   252.2 2920.18   264.5 2919.77
   276.8 2920.55   293.4 2918.14   308.8 2917.57   330.8  2915.5   350.3 2914.91
   354.9 2914.31   360.8 2914.92   368.7 2915.34   381.3 2915.32     396 2916.44
   403.3 2918.02   410.2 2921.07   419.4 2926.06   422.3 2926.91   433.2 2928.11
   459.4 2929.61   485.6 2935.29   501.1 2938.14   508.5 2939.08   511.1 2939.83
#Mann= 6 ,-1,0
       0     .06       0      50      .1       0     120     .06       0
   350.3    .045       0   360.8     .06       0  511.08      .1       0
#XS Ineff= 1 ,-1
  374.11511.0825 2917.27
Permanent Ineff=
       F
Bank Sta=350.3,360.8
XS Rating Curve= 0 ,0
Exp/Cntr(USF)=0,0
Exp/Cntr=0.3,0.1

Type RM Length L Ch R = 1 ,864     ,123.7,126.5,121.9
XS GIS Cut Line= 5
2355557.67409291 657095.785768322355496.59230269657323.667831837
2355488.31473984657388.2969306392355472.26825554 657521.70812367
2355592.83140324657571.216497404
#Sta/Elev= 30
       0  2929.9      47 2927.46   117.4 2926.53   149.3 2924.78   160.3 2924.71
   168.9 2923.54   188.5 2918.08   206.6 2916.15   266.2 2915.08   281.8 2915.69
   305.6 2915.56   312.92912.455   318.1 2912.06   323.32912.862   334.2 2913.38
   374.5 2913.08   382.5 2914.02   393.5 2912.63   410.8    2912   414.8 2912.11
   424.3 2914.31   439.7 2914.78   456.4 2914.45   465.6 2916.12   474.3  2916.8
   482.9 2919.27   490.2 2920.69   517.5 2923.91   530.5 2928.19   565.8 2934.22
#Mann= 6 ,-1,0
       0     .06       0  321.26    .045       0   331.4     .07       0
  564.44      .1       0  614.44     .06       0  664.44      .1       0
#XS Ineff= 2 , 0
          295.99 2914.27  425.14         2915.27
Permanent Ineff=
       F       F
Bank Sta=312.9,323.3
XS Rating Curve= 0 ,0
Exp/Cntr(USF)=0,0
Exp/Cntr=0.3,0.1

Type RM Length L Ch R = 1 ,738     ,476.6,478.6,469.8
XS GIS Cut Line= 4
2355553.46028297657090.7656945672355393.46816895657216.691725256
 2355394.8217468657546.6418038342355569.08075312657598.382580929
#Sta/Elev= 30
       0 2929.72    47.4 2927.69    88.2 2925.19    93.3 2923.69    99.5 2919.65
   102.3 2918.43     134  2911.6   249.6 2910.73   284.1 2911.76   312.1 2910.69
   328.1 2911.47   348.1    2911   392.1 2911.24     398 2910.41   404.1 2910.05
     410 2910.37   416.1 2911.35   436.1 2911.38   492.1 2910.32   512.1 2911.45
   528.1 2913.43   543.3 2913.21   555.8 2911.78     601 2914.36   622.6 2914.43
   643.5 2917.05     675 2923.78   685.2 2924.58   697.7 2928.71   715.3 2930.98
#Mann= 9 ,-1,0
       0     .06       0  211.65     .05       0  241.65     .07       0
  330.52    .045       0   343.2     .07       0  612.95     .08       0
  712.95      .1       0  817.01     .06       0  917.01      .1       0
#XS Ineff= 2 , 0
          330.78 2913.87  502.73          2914.4
Permanent Ineff=
       F       F
Bank Sta=398,410
XS Rating Curve= 0 ,0
Exp/Cntr(USF)=0,0
Exp/Cntr=0.3,0.1

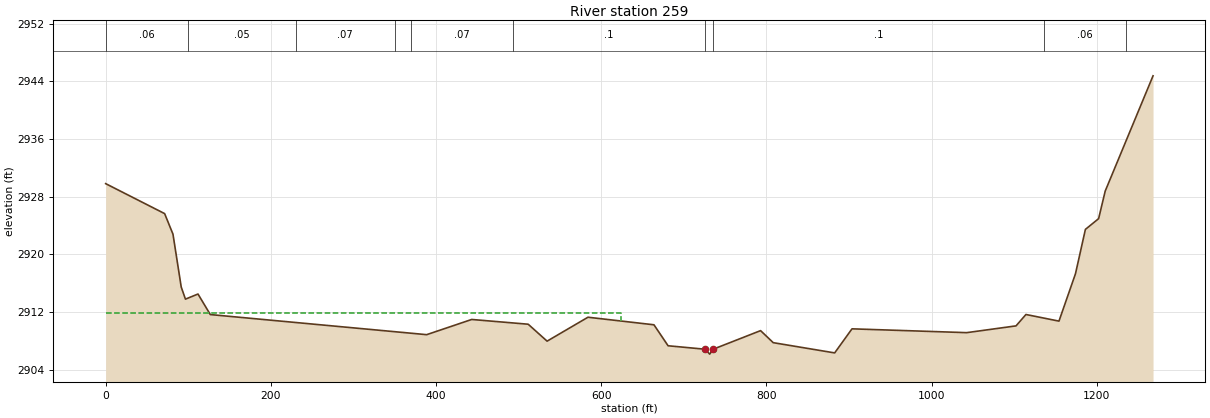
Type RM Length L Ch R = 1 ,259     ,,,
XS GIS Cut Line= 5
2355541.07019639657073.4417051882355188.30458368657341.331381003
2355083.53584908657528.3236794682355299.70425085657748.470640781
2355602.07477603657752.449200323
#Sta/Elev= 30
       0 2929.81    71.4 2925.65    81.5  2922.8    91.5 2915.46    96.6 2913.78
   111.8 2914.49   126.7 2911.64   388.7 2908.85   443.2 2910.96   511.6  2910.3
   534.5 2907.95     584 2911.27   663.9 2910.22     681 2907.31   725.8 2906.83
   731.4 2906.15  735.53 2906.83     793 2909.41   808.3 2907.74   882.7 2906.32
   903.7 2909.66  1042.6 2909.13  1102.3 2910.07  1114.3 2911.65  1154.3 2910.73
  1174.3 2917.31  1186.3 2923.46  1202.3 2924.95  1210.3 2928.78  1268.2 2944.77
#Mann= 10 ,-1,0
       0     .06       0     100     .05       0     230     .07       0
     350      .1       0     370     .07       0  492.95      .1       0
   725.8    .045       0  735.53      .1       0 1135.83     .06       0
 1235.83      .1       0
#XS Ineff= 2 , 0
          623.63 2911.81
Permanent Ineff=
       F       F
Bank Sta=725.8,735.53
XS Rating Curve= 0 ,0
Exp/Cntr(USF)=0,0
Exp/Cntr=0.3,0.1
LCMann Table=0

Chan Stop Cuts=-1
Use User Specified Reach Order=0
Composite Channel Slope=5